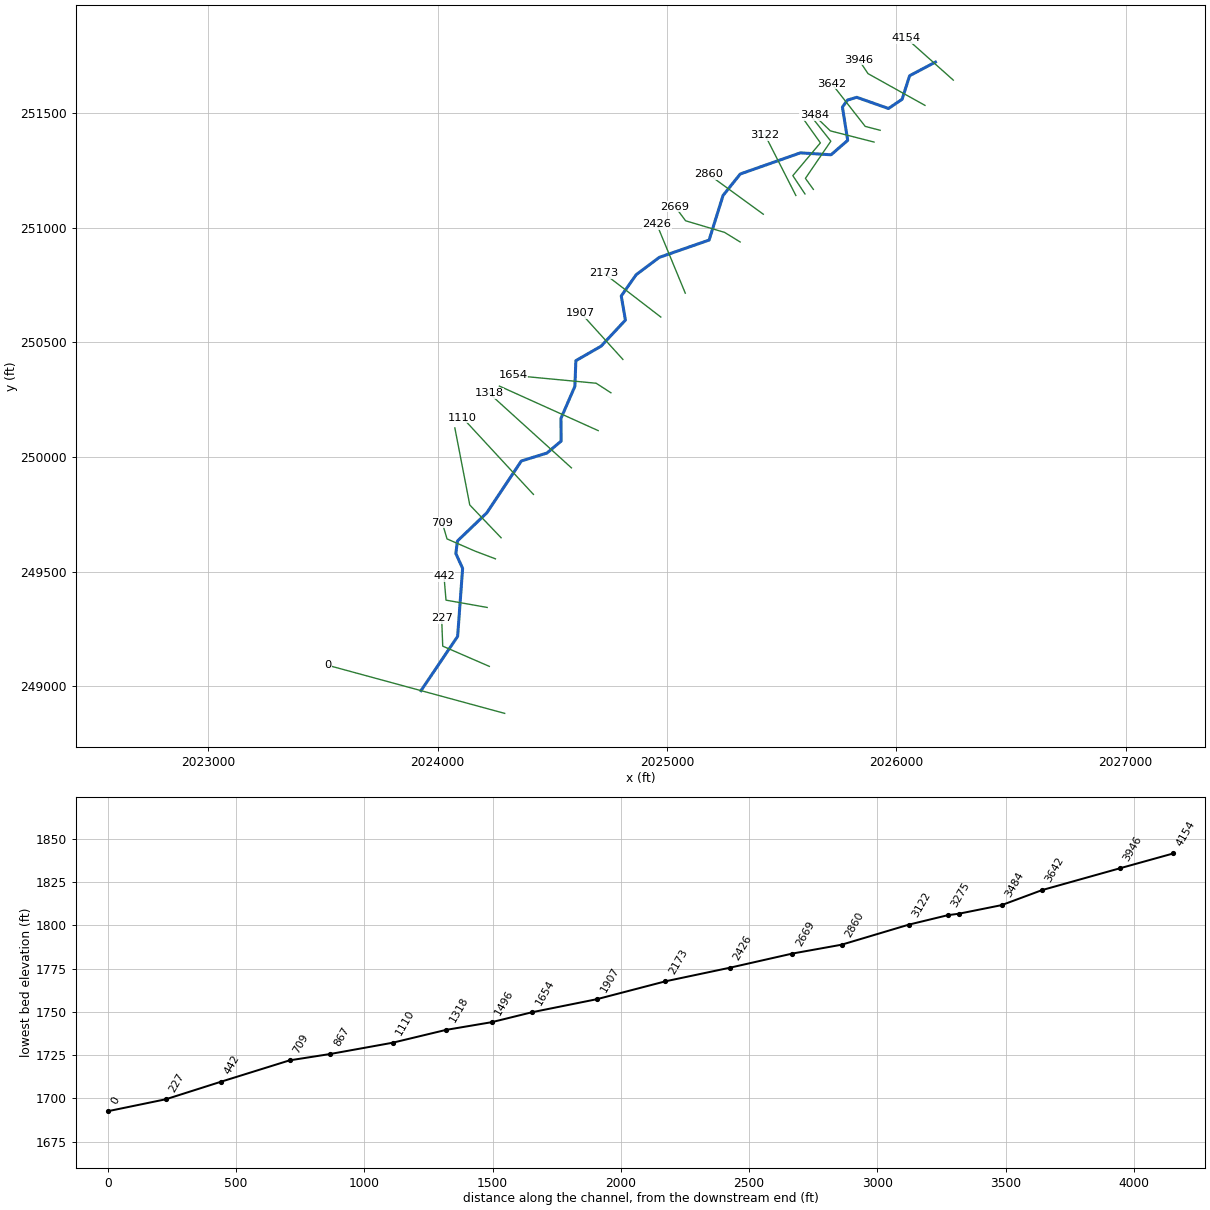
--- BIGCK_2.prj (project) ---

Proj Title=BIGCK_2
Current Plan=p01
Default Exp/Contr=0,0
English Units
Geom File=g01
Flow File=f01
Plan File=p01
BEGIN DESCRIPTION:
Stream Name: Big Creek 2
Flood Zone: Approximate
Summers County, West Virginia
HEC-RAS Version: 5.0.7
Hydrology Method:
regression
Model Notes:
KWSEL - coincident peak with BIGCK_T1 (shared XS with BIGCK_1)
The 100 plus and 500-yr profiles are crossing where hydrology methodology switches from regression to gage weighting at the tie in with Big Creek 1
END DESCRIPTION:
DSS Export Rating Curves= 0
DSS Export Rating Curve Sorted= 0
DSS Export Volume Flow Curves= 0
DXF OffsetX= 0
DXF OffsetY= 0
DXF ScaleX= 0
DXF ScaleY= 0

--- BIGCK_2.p01 (plan) ---

Plan Title=Floodplain
Program Version=5.07
Short Identifier=Floodplain
Geom File=g01
Flow File=f01
Subcritical Flow
K Sum by GR= 0
Std Step Tol= 0.01
Critical Tol= 0.01
Num of Std Step Trials= 20
Max Error Tol= 0.3
Flow Tol Ratio= 0.001
Split Flow NTrial= 30
Split Flow Tol= 0.02
Split Flow Ratio= 0.02
Log Output Level= 0
Friction Slope Method= 1
Unsteady Friction Slope Method= 2
Unsteady Bridges Friction Slope Method= 1
Parabolic Critical Depth
Global Vel Dist= 0 , 0 , 0
Global Log Level= 0
CheckData=True
Encroach Param=-1 ,0,0, 0
Mapping Interval=1HOUR
Computation Time Step Use Courant=        0
Computation Time Step Use Time Series=    0
Computation Time Step Count To Double=0
Computation Time Step Max Doubling=0
Computation Time Step Max Halving=0
Computation Time Step Residence Courant=0
Run HTab= 0
Run UNet= 0
Run Sediment= 0
Run PostProcess= 0
Run WQNet= 0
Run RASMapper= 0
UNET Theta= 0
UNET Theta Warmup= 0
UNET ZTol= 0
UNET ZSATol= 0
UNET MxIter= 0
UNET Max Iter WO Improvement= 0
UNET MaxInSteps= 0
UNET DtIC= 0
UNET DtMin= 0
UNET MaxCRTS= 0
UNET WFStab= 0
UNET SFStab= 0
UNET WFX= 1
UNET SFX= 1
UNET 1D Methodology=Finite Difference
UNET DSS MLevel= 1
UNET Pardiso=0
UNET DZMax Abort= 0
UNET Use Existing IB Tables= 0
UNET Froude Reduction=False
UNET Froude Limit= 0
UNET Froude Power= 0
UNET D1 Cores= 0
UNET D2 Coriolis=0
UNET D2 Cores= 0
UNET D2 Theta= 1
UNET D2 Theta Warmup= 1
UNET D2 Z Tol= 0.01
UNET D2 Volume Tol= 0.01
UNET D2 Max Iterations= 20
UNET D2 Equation= 0
UNET D2 RampUpFraction=0.1
UNET D2 TimeSlices= 1
UNET D2 BCVolumeCheck=0
UNET D1D2 MaxIter= 0
UNET D1D2 ZTol=0.01
UNET D1D2 QTol=0.1
UNET D1D2 MinQTol=1
Write IC File= 0
Write IC File at Fixed DateTime=0
Write IC File at Sim End=0
Echo Input=False
Echo Parameters=False
Echo Output=False
Write Detailed= 0
HDF Write Warmup=0
HDF Write Time Slices=0
HDF Flush=0
HDF Face Node Velocities=0
HDF Compression= 1
HDF Chunk Size= 1
HDF Spatial Parts= 1
HDF Use Max Rows=0
HDF Fixed Rows= 1
Calibration Method= 0
Calibration Iterations= 20
Calibration Max Change=0.05
Calibration Tolerance=0.2
Calibration Maximum=1.5
Calibration Minimum=0.5
Calibration Optimization Method= 1
WQ AD Non Conservative
WQ ULTIMATE=-1
WQ Max Comp Step=1HOUR
WQ Output Interval=15MIN
WQ Output Selected Increments= 0
WQ Output face flow=0
WQ Output face velocity=0
WQ Output face area=0
WQ Output face dispersion=0
WQ Output cell volume=0
WQ Output cell surface area=0
WQ Output cell continuity=0
WQ Output cumulative cell continuity=0
WQ Output face conc=0
WQ Output face dconc_dx=0
WQ Output face courant=0
WQ Output face peclet=0
WQ Output face adv mass=0
WQ Output face disp mass=0
WQ Output cell mass=0
WQ Output cell source sink temp=0
WQ Output nsm pathways=0
WQ Output nsm derived pathways=0
WQ Output MaxMinRange=-1
WQ Daily Max Min Mean=-1
WQ Daily Range=0
WQ Daily Time=0
WQ Create Restart=0
WQ Fixed Restart=0
WQ System Summary=0
WQ Write To DSS=0
WQ Use Fixed Temperature=0
Sorting and Armoring Iterations= 10
XS Update Threshold= 0.02
Bed Roughness Predictor= 0
Hydraulics Update Threshold= 0.02
Energy Slope Method= 1
Volume Change Method= 1
Sediment Retention Method= 0
XS Weighting Method= 0
Number of US Weighted Cross Sections= 1
Number of DS Weighted Cross Sections= 1
Upstream XS Weight=0
Main XS Weight=1
Downstream XS Weight=0
Number of DS XS's Weighted with US Boundary= 1
Upstream Boundary Weight= 1
Weight of XSs Associated with US Boundary= 0
Number of US XS's Weighted with DS Boundary= 1
Downstream Boundary Weight= 0.5
Weight of XSs Associated with DS Boundary= 0.5
Percentile Method= 0
Sediment Output Level= 3
Mass or Volume Output= 0
Output Increment Type= 1
Profile and TS Output Increment= 1
XS Output Flag= 0
XS Output Increment= 10
Write Gradation File= 0
Read Gradation Hotstart= 0
Write HDF5 File= 1
Write Binary Output= 1
Write DSS Sediment File= 0
SV Curve= 0
Specific Gage Flag= 0

--- BIGCK_2.f01 (steady flow) ---

Flow Title=Flows
Program Version=5.07
Number of Profiles= 6
Profile Names=01pct,10pct,04pct,02pct,0_2pct,01plus
River Rch & RM=BIGCK_2,Main            ,4154
     564     298     396     478     788     835
River Rch & RM=BIGCK_2,Main            ,0
    2463    1138    1610    2014    3720    3506
Boundary for River Rch & Prof#=BIGCK_2,Main            , 1
Up Type= 0
Dn Type= 1
Dn Known WS=1698.3
Boundary for River Rch & Prof#=BIGCK_2,Main            , 2
Up Type= 0
Dn Type= 1
Dn Known WS=1696.6
Boundary for River Rch & Prof#=BIGCK_2,Main            , 3
Up Type= 0
Dn Type= 1
Dn Known WS=1697.1
Boundary for River Rch & Prof#=BIGCK_2,Main            , 4
Up Type= 0
Dn Type= 1
Dn Known WS=1697.7
Boundary for River Rch & Prof#=BIGCK_2,Main            , 5
Up Type= 0
Dn Type= 1
Dn Known WS=1700.2
Boundary for River Rch & Prof#=BIGCK_2,Main            , 6
Up Type= 0
Dn Type= 1
Dn Known WS=1699.9
DSS Import GetInterval= 0
DSS Import GetPeak= 0
DSS Import FillOption= 0

--- BIGCK_2.g01 (geometry) ---

Geom Title=Geometry
Program Version=5.07

River Reach=BIGCK_2         ,Main
Reach XY= 30
2026170.91540931251722.2296005172026058.26938137251662.743783506
2026025.57758591251560.0125419862025966.20074891251519.805701838
2025827.64822694251568.6608352772025787.28952491251556.605638568
2025765.27568745251525.9435078082025788.24499999251380.976999905
2025715.77099999251317.9559999182025581.92040296251326.406009992
     2025319.702251234.1819999132025244.63465161251140.561261196
     2025183.781 250945.96999991     2024966.403250870.465999906
2024865.70899999250794.9459999122024800.60499999250702.063999911
     2024818.834250597.028999906     2024712.931250483.313999915
2024602.68799999 250419.945999912024598.34799999250307.966999915
     2024537.584 250168.209999912024538.45199999250069.250999913
2024476.81999999250017.167999908     2024364.841249982.445999918
2024214.11299999249756.1499999092024086.19499999249633.486999911
2024079.17421961249578.7999999072024108.74699999249514.015999912
     2024086.956249217.4539999162023927.23448476248980.838642198

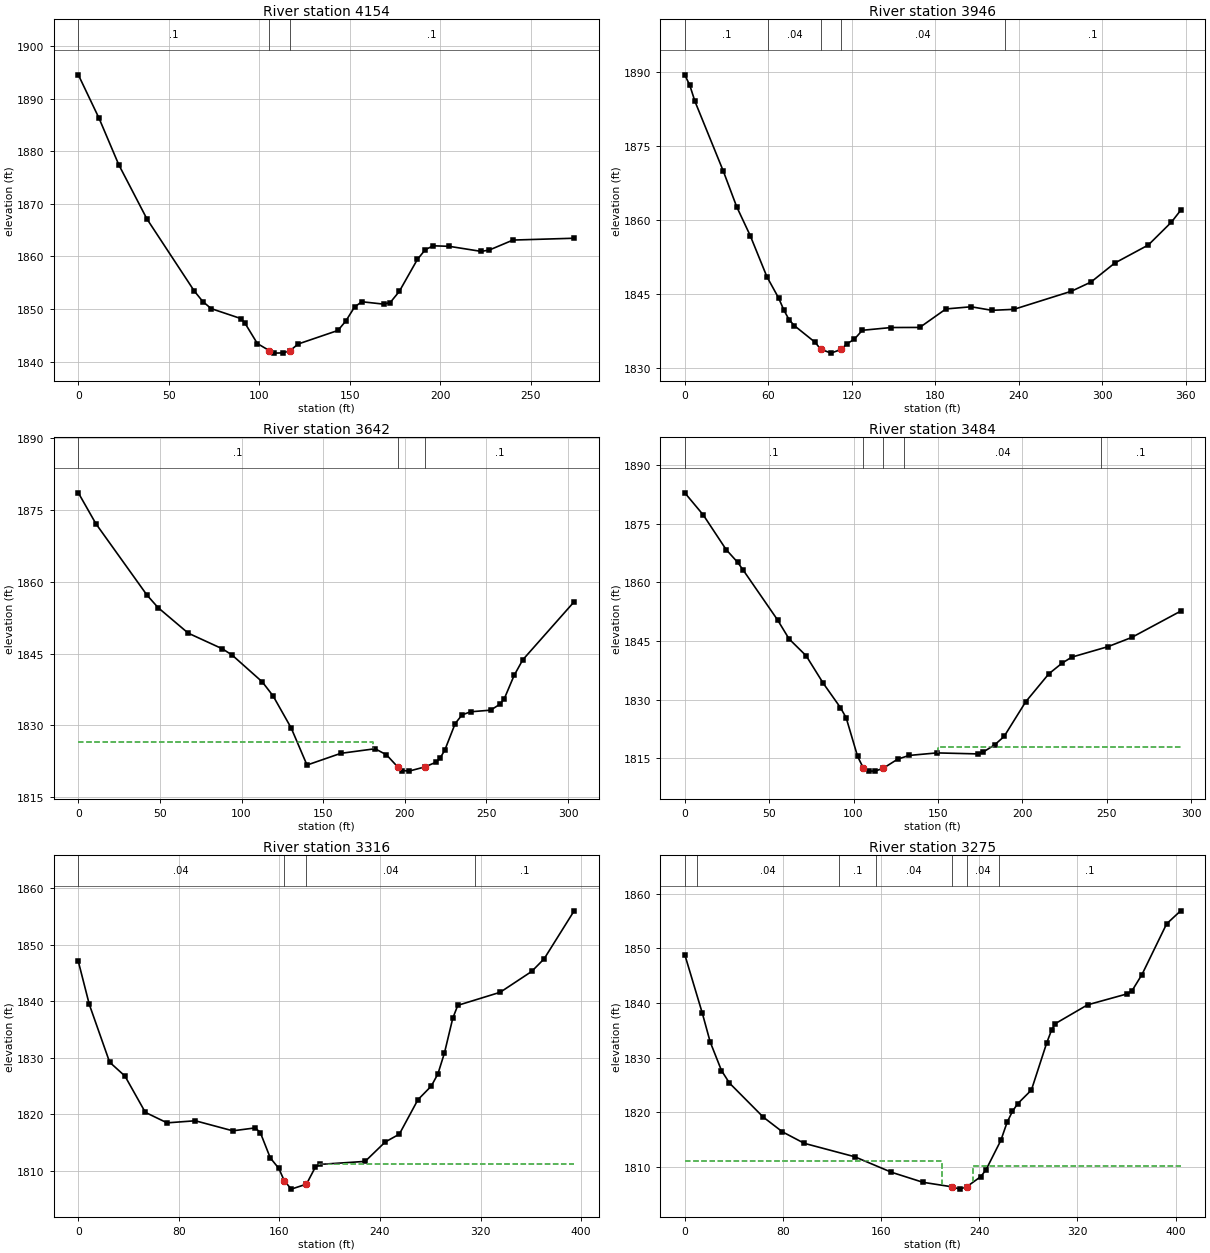
Type RM Length L Ch R = 1 ,4154    ,207.6,207.6,207.6
XS GIS Cut Line= 2
2026248.90863314251643.5649629532026044.48154983251825.856629595
#Sta/Elev= 30
       0 1894.52    11.5 1886.22    22.3 1877.46    37.9 1867.12    64.1  1853.4
    68.8 1851.41    73.4 1850.08    89.7  1848.2      92 1847.34    98.9 1843.44
  105.59 1842.08   108.2 1841.62   113.2 1841.67     117 1842.09   121.4 1843.35
   143.4 1845.93   147.8 1847.74   152.6 1850.39   156.6 1851.39   168.7 1850.93
   172.3 1851.24   177.3 1853.35   187.3 1859.43   191.7  1861.3   196.1 1862.02
   204.9 1861.92   222.5 1860.96   226.9  1861.2   240.1 1863.11 273.899 1863.46
#Mann= 3 ,-1 , 0
       0      .1       0  105.59    .045       0     117      .1       0
Bank Sta=105.59,117
XS Rating Curve= 0 ,0
Exp/Cntr(USF)=0,0
Exp/Cntr=0.3,0.1

Type RM Length L Ch R = 1 ,3946    ,308.3,304.3,300
XS GIS Cut Line= 3
2026125.32920337251533.481886595 2025877.0538888251671.801081643
2025837.12333328251731.696914971
#Sta/Elev= 30
       0 1889.38     3.6 1887.25     7.3    1884    27.7 1869.87    37.3 1862.67
      47 1856.85      59 1848.52    67.4 1844.22    71.2 1841.76    74.9 1839.84
    78.7 1838.63    93.7 1835.24    97.5 1833.89     105 1833.07   112.5 1833.84
   116.2 1834.92   121.7 1835.85   127.5 1837.69   148.3 1838.25   168.8 1838.27
   187.6 1842.01   205.7 1842.45   220.6 1841.73   236.4 1841.93   277.7 1845.59
   291.8 1847.45   308.8 1851.28     333 1854.95   349.6 1859.58356.1914 1861.96
#Mann= 5 ,-1 , 0
       0      .1       0      60     .04       0    97.5    .045       0
   112.5     .04       0     230      .1       0
Bank Sta=97.5,112.5
XS Rating Curve= 0 ,0
Exp/Cntr(USF)=0,0
Exp/Cntr=0.3,0.1

Type RM Length L Ch R = 1 ,3642    ,147.7,157.8,167.5
XS GIS Cut Line= 3
2025929.89821649251424.8149629532025864.79404983251441.742046267
2025718.96071652251627.939962938
#Sta/Elev= 30
       0 1878.62    10.8 1872.14      42 1857.26    48.8 1854.63    67.3 1849.28
    88.3 1845.99    94.3 1844.67   112.7 1839.08   119.3 1836.16   130.4 1829.45
   140.1 1821.69   160.8 1824.14   181.8  1825.1   188.8 1823.83   195.8 1821.25
   198.4 1820.55   202.6 1820.42   212.2 1821.29   219.1 1822.27   221.6 1823.13
   224.5 1824.79   230.9 1830.38   235.1 1832.18   240.3 1832.83   252.6 1833.17
   258.3 1834.41     261 1835.59     267 1840.44   272.3  1843.7303.7788 1855.84
#Mann= 3 ,-1 , 0
       0      .1       0   195.8    .045       0   212.2      .1       0
#XS Ineff= 2 , 0
          180.48 1826.52
Permanent Ineff=
       F       F
Bank Sta=195.8,212.2
XS Rating Curve= 0 ,0
Exp/Cntr(USF)=0,0
Exp/Cntr=0.3,0.1

Type RM Length L Ch R = 1 ,3484    ,191.8,168,145.4
XS GIS Cut Line= 3
2025903.16857129251373.4692976962025712.63793804251422.200403057
2025642.73676231251489.704967041
#Sta/Elev= 30
       0 1882.86      11 1877.17    24.5 1868.35    31.3  1865.1    34.7 1863.05
      55 1850.35    61.8 1845.51    71.9 1841.21    82.1 1834.14    92.2 1827.97
    95.6 1825.38   102.4 1815.47   105.8  1812.5   109.2 1811.73   112.6 1811.72
   117.4  1812.4   126.1 1814.77   132.9 1815.73   149.4 1816.38   173.5 1816.12
   176.9 1816.61   183.7 1818.47   189.2 1820.58     202 1829.44   215.7 1836.59
   223.6 1839.34   229.3 1840.86   250.7 1843.53   264.8 1845.89   293.8 1852.61
#Mann= 5 ,-1 , 0
       0      .1       0   105.8    .045       0   117.4      .1       0
     130     .04       0  246.66      .1       0
#XS Ineff= 2 , 0
                             150            1818
Permanent Ineff=
       F       F
Bank Sta=105.8,117.4
XS Rating Curve= 0 ,0
Exp/Cntr(USF)=0,0
Exp/Cntr=0.5,0.3

Type RM Length L Ch R = 1 ,3316    ,41,40.9,40.8
XS GIS Cut Line= 4
2025638.42699563251167.1936259782025603.85947642251215.026822129
2025714.69944461251377.1928755572025628.40173063251486.180616401
#Sta/Elev= 30
       0 1847.01     8.7 1839.42    24.9 1829.18    37.1 1826.72    53.3  1820.3
    70.6 1818.44    93.1 1818.81   122.9 1817.03   140.8 1817.55   144.8 1816.72
   152.7 1812.25   159.5 1810.38   163.81808.223   169.4 1806.71   181.5 1807.59
   188.5 1810.57   192.5 1811.09   228.2 1811.62   244.1 1815.04   255.4 1816.44
   270.2 1822.54   280.8 1824.94   286.1 1827.11   291.3 1830.81   297.9 1836.94
   301.9 1839.24   335.6 1841.55   360.7 1845.24   370.6 1847.47   394.5 1855.97
#Mann= 4 ,-1 , 0
       0     .04       0   163.8    .045       0   181.5     .04       0
  315.44      .1       0
#XS Ineff= 2 , 0
           153.8  1811.8   191.5          1811.2
Permanent Ineff=
       F       F
Bank Sta=163.8,181.5
XS Rating Curve= 0 ,0
Exp/Cntr(USF)=0,0
Exp/Cntr=0.5,0.3

Type RM Length L Ch R = 1 ,3275    ,140,152.8,166.8
XS GIS Cut Line= 4
2025601.88315159251147.2304809112025548.84949744251226.944450321
2025669.09949144251369.8743800872025598.73455031251469.037064001
#Sta/Elev= 30
       0 1848.84    14.3 1838.12    20.7 1832.87    29.9 1827.64    36.4 1825.35
      64 1819.11    79.6 1816.42    97.4 1814.32   138.4 1811.87   168.4 1809.03
   194.1 1807.19   217.61806.368   224.1 1805.94   229.91806.392   241.3 1808.24
   245.6 1809.53   257.6 1814.87   262.7 1818.18     267 1820.16   271.3 1821.57
   282.5 1824.08   294.9 1832.66   298.9 1835.04     302 1836.23   328.3 1839.67
   360.5 1841.67   364.5 1842.25   372.6 1845.21   392.7 1854.49   404.1 1856.87
#Mann= 7 ,-1 , 0
       0      .1       0      10     .04       0  125.74      .1       0
  155.74     .04       0   217.6    .045       0   229.9     .04       0
  255.74      .1       0
#XS Ineff= 2 , 0
             210    1811     235          1810.1
Permanent Ineff=
       F       F
Bank Sta=217.6,229.9
XS Rating Curve= 0 ,0
Exp/Cntr(USF)=0,0
Exp/Cntr=0.5,0.3

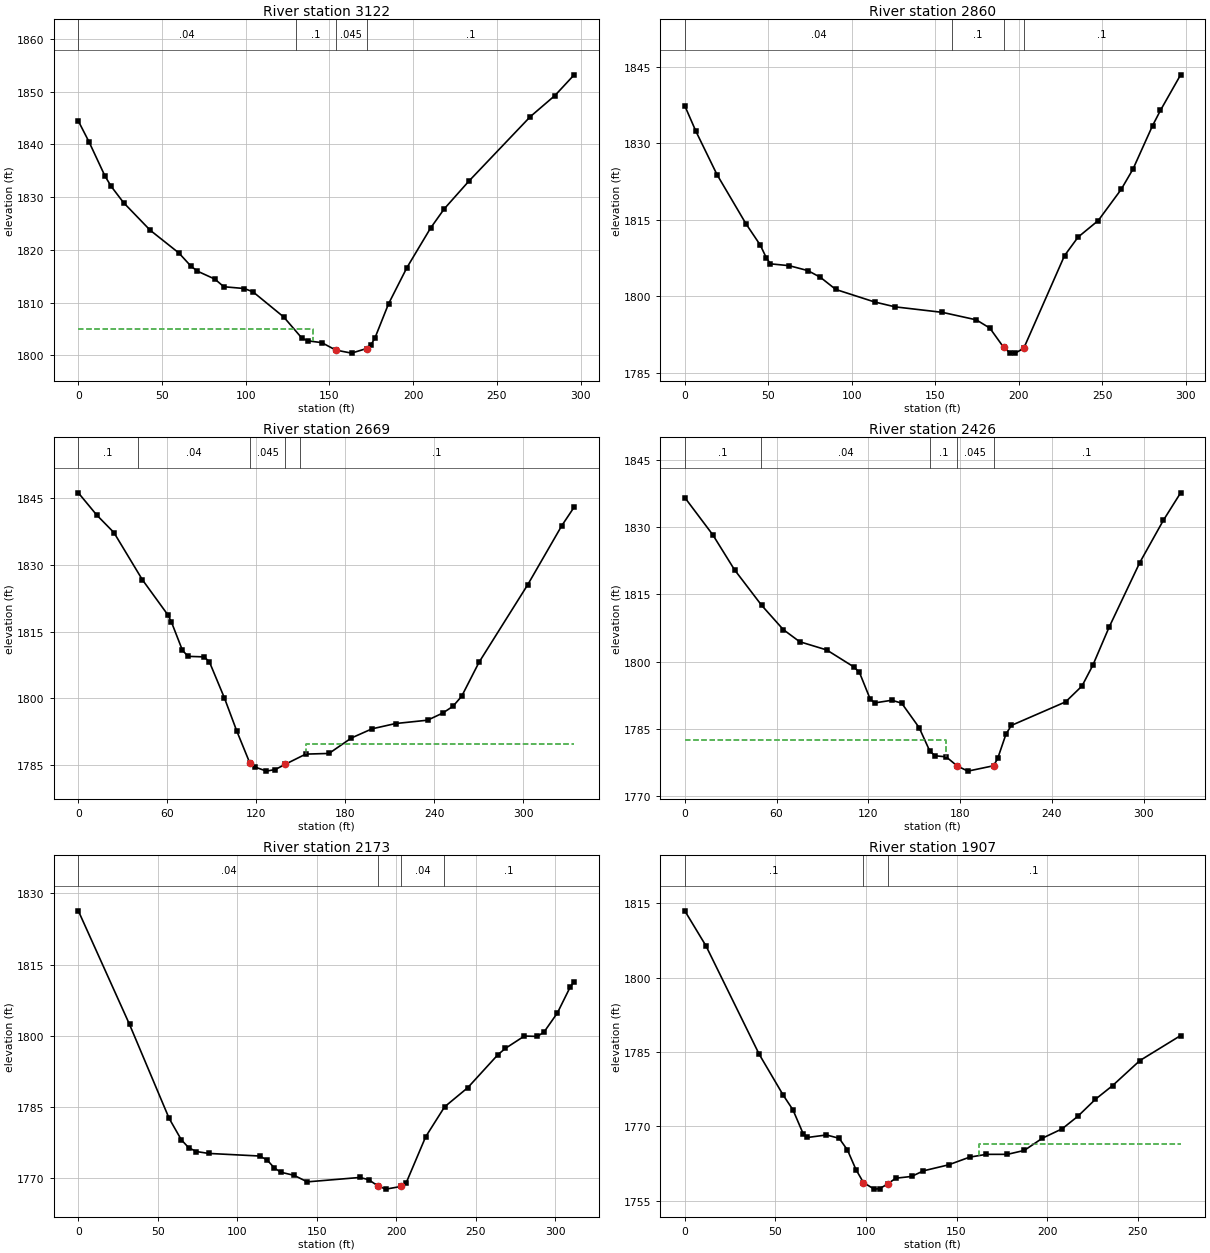
Type RM Length L Ch R = 1 ,3122    ,258.7,262,268.4
XS GIS Cut Line= 2
2025562.11810585251140.4212285832025427.66379167251404.319137165
#Sta/Elev= 30
       0 1844.45     6.4 1840.49    15.9 1834.03    19.6 1832.07      27 1828.98
    42.9 1823.75    60.1 1819.42    67.3 1816.92    71.1 1815.99    81.6 1814.47
    86.9 1813.03    99.1 1812.69   104.3 1812.07   122.7 1807.29   133.7 1803.23
   137.4 1802.76   145.4 1802.43   153.8 1801.02   163.2 1800.44   172.2 1801.31
   174.7 1801.97   177.1 1803.24   185.3 1809.78   196.3 1816.66   210.4 1824.14
   218.6  1827.8   233.3 1833.05     270 1845.28   284.7 1849.28   296.2 1853.21
#Mann= 4 ,-1 , 0
       0     .04       0     130      .1       0   153.8    .045       0
   172.2      .1       0
#XS Ineff= 2 , 0
             140    1805
Permanent Ineff=
       F       F
Bank Sta=153.8,172.2
XS Rating Curve= 0 ,0
Exp/Cntr(USF)=0,0
Exp/Cntr=0.3,0.1

Type RM Length L Ch R = 1 ,2860    ,188.8,191.5,196.2
XS GIS Cut Line= 2
2025420.18828139251058.7854078352025180.12767218251233.338629501
#Sta/Elev= 30
       0 1837.37     6.7 1832.33    19.3 1823.86    36.6 1814.23    45.2 1810.03
    48.8 1807.54    51.3 1806.36    62.5    1806    73.7 1805.03    81.2 1803.71
    90.4 1801.33   113.7 1798.87   125.9 1797.92   154.2 1796.84   174.5 1795.37
   182.6 1793.75   190.8    1790   190.8 1789.99   190.8 1789.98   194.8 1788.86
   197.8 1788.84   202.9 1789.79   227.3 1807.97   235.4  1811.6   247.5 1814.86
   261.2 1820.96   268.3 1824.96     280 1833.48   284.7 1836.46   296.8 1843.45
#Mann= 4 ,-1 , 0
       0     .04       0     160      .1       0   190.8    .045       0
   202.9      .1       0
Bank Sta=190.8,202.9
XS Rating Curve= 0 ,0
Exp/Cntr=0.3,0.1

Type RM Length L Ch R = 1 ,2669    ,259.4,242.7,229.5
XS GIS Cut Line= 4
2025319.13115305250937.7565150092025251.29593725250979.476836491
2025081.26151656251030.1244872192025035.13266197251092.337972183
#Sta/Elev= 30
       0 1846.07    12.4  1841.1      24 1837.17    43.2  1826.6    60.4 1818.73
    62.8 1817.13    70.2 1810.82      74 1809.44    84.9 1809.32    88.4 1808.22
    98.6 1800.08   106.9  1792.7   115.81785.458     119 1784.67   126.9 1783.73
   132.9 1784.09   139.7 1785.28   153.4 1787.54   169.1 1787.69   184.2 1791.15
   198.1  1793.2     214 1794.39   235.6 1795.14   245.8 1796.73   252.7 1798.24
   258.6 1800.49   270.3  1808.1   303.2  1825.5   326.2 1838.74   334.5 1842.87
#Mann= 5 ,-1 , 0
       0      .1       0      40     .04       0   115.8    .045       0
   139.7     .04       0  149.64      .1       0
#XS Ineff= 2 , 0
                          153.73         1789.82
Permanent Ineff=
       F       F
Bank Sta=115.8,139.7
XS Rating Curve= 0 ,0
Exp/Cntr=0.3,0.1

Type RM Length L Ch R = 1 ,2426    ,245.7,252.8,261.3
XS GIS Cut Line= 2
2025079.86941443250714.4721879812024956.04447458251014.048655371
#Sta/Elev= 30
       0  1836.6    18.3  1828.3    32.5  1820.5    50.2 1812.58    64.4 1807.15
    75.1 1804.45    92.8 1802.61   110.6 1798.81   114.2 1797.59   121.2 1791.67
   124.2  1790.8   135.4 1791.39   141.8 1790.74   153.2  1785.3   160.3 1779.97
   163.8    1779   170.9 1778.77   178.11776.734   185.1 1775.58   201.91776.781
   204.6 1778.42     210 1783.83   213.5 1785.77     249 1791.03   259.7 1794.56
   266.8  1799.2   277.4 1807.66   297.5 1822.11   312.9 1831.52   324.2 1837.66
#Mann= 5 ,-1 , 0
       0      .1       0      50     .04       0     160      .1       0
   178.1    .045       0   201.9      .1       0
#XS Ineff= 2 , 0
           170.5 1782.53
Permanent Ineff=
       F       F
Bank Sta=178.1,201.9
XS Rating Curve= 0 ,0
Exp/Cntr=0.3,0.1

Type RM Length L Ch R = 1 ,2173    ,268.7,266.9,265.4
XS GIS Cut Line= 2
2024973.22019204 250610.219577332024725.96974762  250800.3507753
#Sta/Elev= 30
       0 1826.34    32.2 1802.39    57.1 1782.59    64.8 1778.05    69.5 1776.37
    74.2 1775.59    81.9 1775.19     114 1774.64   118.7 1773.83   123.3 1772.12
   127.4 1771.22   135.7 1770.57     144 1769.19   177.1 1770.12   182.6 1769.65
   188.8 1768.26   193.5 1767.66   202.9 1768.22   206.1 1768.87   218.5  1778.7
   230.4 1785.01     245 1789.06     264 1796.03   268.7 1797.35   280.6 1799.94
   288.8 1799.86     293 1800.81   301.3 1804.78   309.5 1810.33   311.9 1811.41
#Mann= 4 ,-1 , 0
       0     .04       0   188.8    .045       0   202.9     .04       0
     230      .1       0
Bank Sta=188.8,202.9
XS Rating Curve= 0 ,0
Exp/Cntr(USF)=0,0
Exp/Cntr=0.3,0.1

Type RM Length L Ch R = 1 ,1907    ,240.8,252.9,263.7
XS GIS Cut Line= 2
2024807.85398204250425.2810381272024624.11374871250628.194165373
#Sta/Elev= 30
       0  1813.5    11.7 1806.42    41.1 1784.53    54.4 1776.26    59.7 1773.34
    65.4 1768.47    67.7 1767.76    78.2 1768.27    85.2  1767.6    89.8 1765.23
    94.5 1761.27    98.61758.677   104.5 1757.34   107.5 1757.43   111.91758.361
   116.4 1759.54   125.2  1759.9   131.7 1761.03   145.6 1762.24   157.2 1763.79
   166.5 1764.36   178.1 1764.36   187.4 1765.15   197.4 1767.62   208.3 1769.51
     217 1772.05   226.7 1775.48   236.2 1778.25   251.2 1783.28   273.7 1788.33
#Mann= 3 ,-1 , 0
       0      .1       0    98.6    .045       0   111.9      .1       0
#XS Ineff= 2 , 0
                          162.64         1766.46
Permanent Ineff=
       F       F
Bank Sta=98.6,111.9
XS Rating Curve= 0 ,0
Exp/Cntr=0.3,0.1

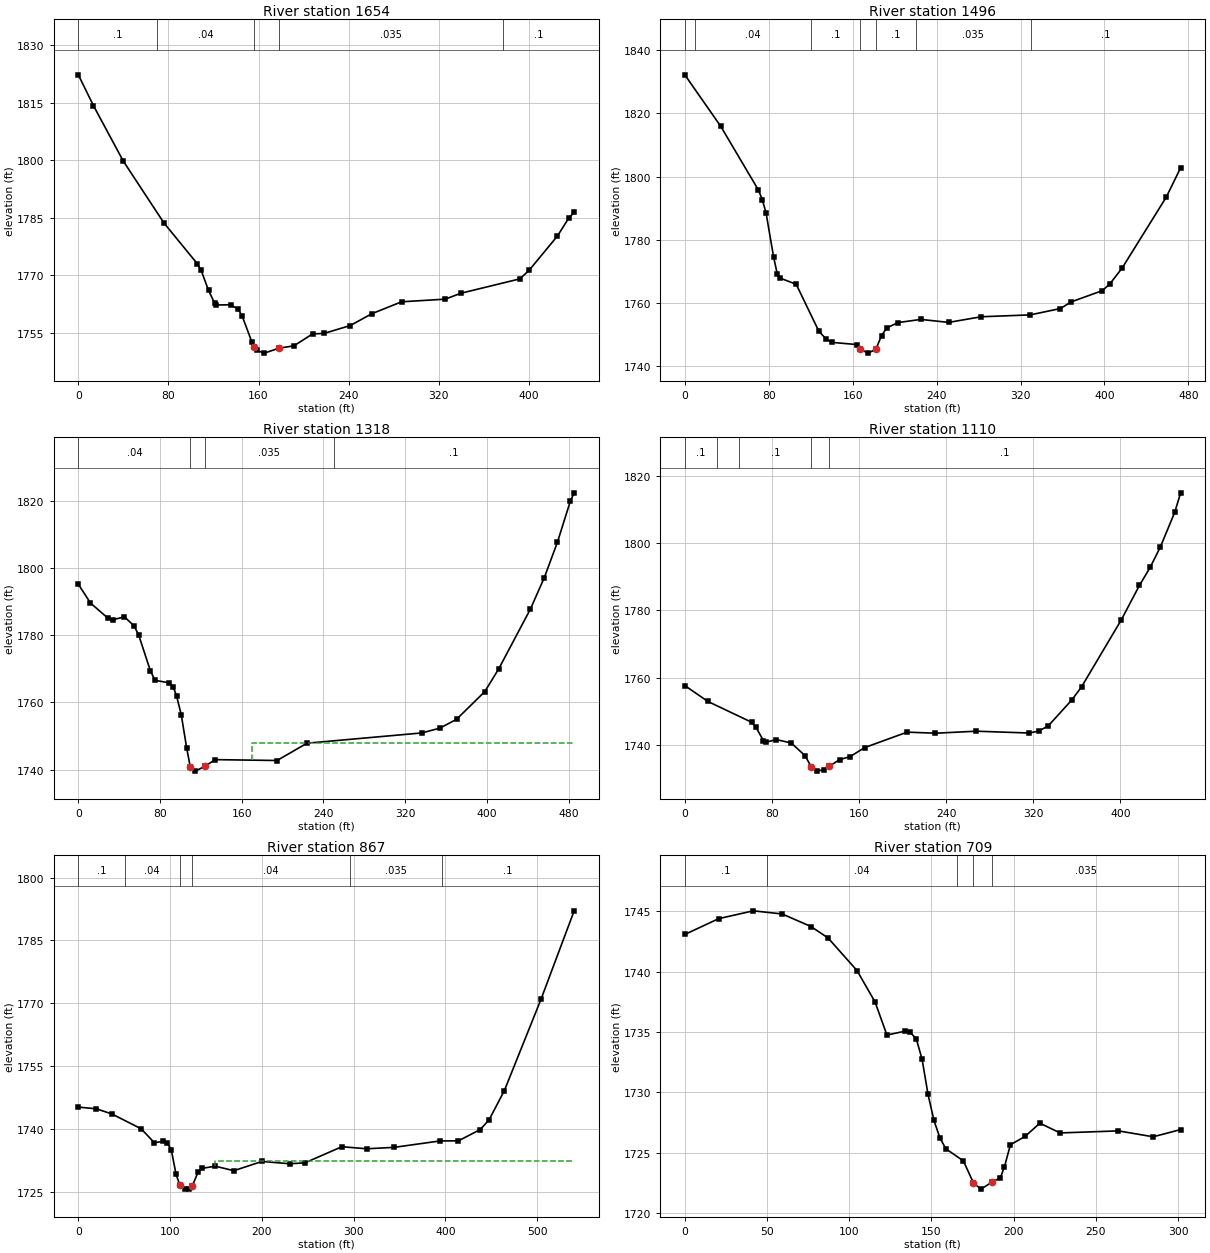
Type RM Length L Ch R = 1 ,1654    ,162.6,157.8,151.8
XS GIS Cut Line= 3
2024755.52795907250279.8865926212024691.12994318250321.557345046
2024329.20147398250355.791282927
#Sta/Elev= 30
       0 1822.23    13.4 1814.22    39.9 1799.78      76 1783.68   105.7 1773.03
     109 1771.36   115.6 1766.12     121 1762.79   122.2 1762.32   135.4 1762.38
     142 1761.17   145.3 1759.55   154.1 1752.67   156.4 1751.41   158.5 1750.48
   165.1 1749.79   178.11751.078   191.4 1751.69   207.9 1754.78   218.3 1754.93
   241.4 1756.97   260.6 1760.05     287 1763.15   325.7 1763.84   339.7 1765.38
     392 1769.12   400.3 1771.38   425.4 1780.29   435.3 1784.89   440.2 1786.46
#Mann= 5 ,-1 , 0
       0      .1       0      70     .04       0   156.4    .045       0
   178.1    .035       0   376.7      .1       0
Bank Sta=156.4,178.1
XS Rating Curve= 0 ,0
Exp/Cntr=0.3,0.1

Type RM Length L Ch R = 1 ,1496    ,180.4,177.6,173
XS GIS Cut Line= 2
2024700.00645378250114.9198179112024269.17925171250309.143010406
#Sta/Elev= 30
       0 1832.23    34.2 1815.94    70.2 1795.71    73.8 1792.71    77.4 1788.55
    84.6  1774.6    88.2 1768.99    90.3 1767.87   106.2 1765.85   127.8 1750.95
     135  1748.4   139.9 1747.45   163.8 1746.75   167.3  1745.3   174.6 1744.03
   182.1 1745.22   187.5 1749.59   192.6 1752.05   203.4 1753.72     225 1754.71
   251.5 1753.77   282.6 1755.56   329.3 1756.15   358.1 1758.17   368.1 1760.24
   397.9 1763.83   404.9 1765.87   416.9 1771.01   458.9 1793.46   472.6 1802.76
#Mann= 7 ,-1 , 0
       0      .1       0      10     .04       0     120      .1       0
   167.3    .045       0   182.1      .1       0     220    .035       0
     330      .1       0
Bank Sta=167.3,182.1
XS Rating Curve= 0 ,0
Exp/Cntr=0.3,0.1

Type RM Length L Ch R = 1 ,1318    ,207.6,208.1,206
XS GIS Cut Line= 2
2024583.37134914249952.3496549412024223.56265705250278.345901154
#Sta/Elev= 30
       0 1795.18    11.9 1789.59    28.8 1785.13    33.5 1784.58    45.1 1785.49
    54.4 1782.85      59 1780.18    70.6 1769.38    75.1  1766.6    89.2 1765.84
    92.8 1764.72    96.2 1761.96   100.8 1756.33   106.1 1746.44   109.7  1740.7
   114.6 1739.58   123.81741.001   134.1    1743   194.6 1742.74   223.9 1747.89
   336.3 1750.94     354 1752.37   370.3 1754.99     398 1763.24   411.6 1769.99
   442.6 1787.76   456.2  1797.1   469.1 1807.67   481.8 1819.95   485.5 1822.38
#Mann= 4 ,-1 , 0
       0     .04       0   109.7    .045       0   123.8    .035       0
     250      .1       0
#XS Ineff= 2 , 0
                             170            1748
Permanent Ineff=
       F       F
Bank Sta=109.7,123.8
XS Rating Curve= 0 ,0
Exp/Cntr(USF)=0,0
Exp/Cntr=0.3,0.1

Type RM Length L Ch R = 1 ,1110    ,242.4,242.8,243.6
XS GIS Cut Line= 2
2024417.50760548249836.6505096672024108.36971467250171.086025652
#Sta/Elev= 30
       0 1757.64    21.2 1752.91    61.3 1746.73    65.3 1745.24    72.2 1741.28
    74.5 1740.79    84.1 1741.55    97.8 1740.53   110.4 1736.78   116.31733.363
     121 1732.16     128 1732.58   132.81733.612   142.1 1735.58   151.8 1736.47
   165.1 1739.16   204.2 1743.77   230.1 1743.45   267.8 1744.05   316.1 1743.51
   324.9 1744.07   333.8 1745.62   355.5 1753.37   364.5 1757.31   400.8 1777.14
   417.6 1787.49   427.5 1792.88   436.8 1798.94     450 1809.24   455.4 1815.04
#Mann= 5 ,-1 , 0
       0      .1       0      30     .04       0      50      .1       0
   116.3    .045       0   132.8      .1       0
Bank Sta=116.3,132.8
XS Rating Curve= 0 ,0
Exp/Cntr(USF)=0,0
Exp/Cntr=0.3,0.1

Type RM Length L Ch R = 1 ,867     ,155,158.8,163.1
XS GIS Cut Line= 3
2024276.50433166249647.6059420432024139.94041213 249790.59822248
2024074.81950693250126.777753295
#Sta/Elev= 30
       0 1745.23    19.7 1744.82    36.6 1743.59    68.5 1740.05    82.8 1736.74
    92.2 1737.03      97 1736.63   101.3 1735.02   106.5 1729.16   110.8 1726.53
     116 1725.66   120.8 1725.79   124.3  1726.5   130.3 1729.63   135.1 1730.63
   149.3 1731.13   169.4 1730.06   200.2 1732.27   230.3 1731.71     247 1731.94
   287.1 1735.78   314.1 1735.29   343.9 1735.62   394.1 1737.16   414.1 1737.18
   437.9 1739.88   447.5 1742.19   464.2 1749.19   504.2 1771.03   540.2 1792.06
#Mann= 6 ,-1 , 0
       0      .1       0    50.3     .04       0   110.8    .045       0
   124.3     .04       0     296    .035       0   396.2      .1       0
#XS Ineff= 2 , 0
                          149.05         1732.49
Permanent Ineff=
       F       F
Bank Sta=110.8,124.3
XS Rating Curve= 0 ,0
Exp/Cntr=0.3,0.1

Type RM Length L Ch R = 1 ,709     ,265,267,268.4
XS GIS Cut Line= 4
2024251.70666659249555.7217992252024162.29694438249589.575965896
2024040.76916659249642.5273548072024019.93583325249712.839854792
#Sta/Elev= 30
       0 1743.09    20.6  1744.4    41.6 1745.05    59.2 1744.79    76.7 1743.75
    87.1  1742.8   104.7  1740.1   115.7 1737.49   122.9 1734.75   133.6 1735.06
   137.1 1734.97   140.8 1734.42   144.3 1732.73   147.9 1729.83   151.5 1727.67
   155.1 1726.23   158.7 1725.32   169.4 1724.31   175.5 1722.49   180.1 1721.97
   186.9 1722.56   191.9 1722.91   194.4 1723.84     198 1725.65   206.9 1726.34
   215.9 1727.44   228.2 1726.63   263.7  1726.8   284.8 1726.31   301.5 1726.91
#Mann= 5 ,-1 , 0
       0      .1       0      50     .04       0   165.6    .035       0
   175.5    .045       0   186.9    .035       0
Bank Sta=175.5,186.9
XS Rating Curve= 0 ,0
Exp/Cntr(USF)=0,0
Exp/Cntr=0.3,0.1

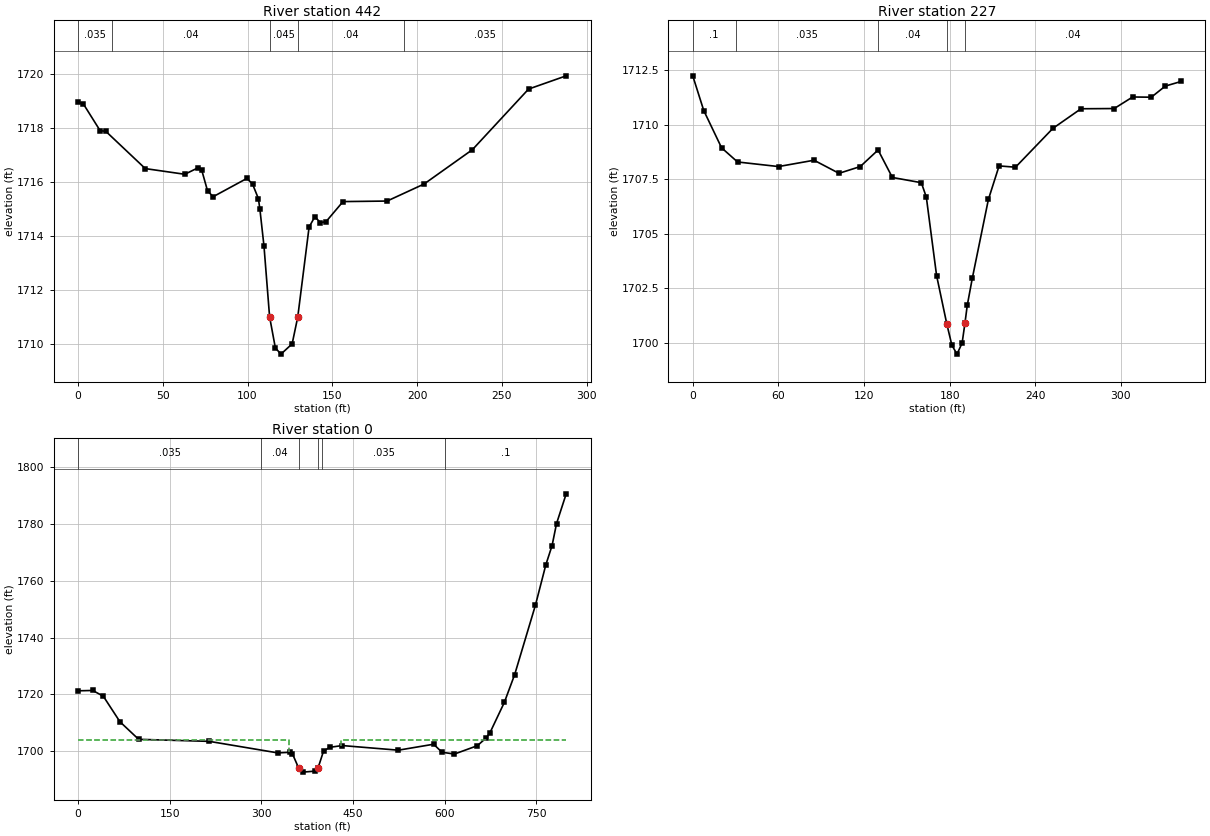
Type RM Length L Ch R = 1 ,442     ,217.3,215,212.6
XS GIS Cut Line= 3
2024215.77272152249343.6494770692024036.30020985249375.470844386
2024027.39247239249480.709284709
#Sta/Elev= 30
       0 1718.94     3.1 1718.89    13.1 1717.89    16.4 1717.87    39.7 1716.49
      63 1716.28    70.5 1716.51      73 1716.43    76.4 1715.67    79.7 1715.45
    99.7 1716.13     103 1715.91   106.4 1715.38   107.3 1714.98   109.7 1713.62
     113 1711.01   116.4 1709.86   119.7 1709.63   126.3 1710.01   129.6    1711
   136.3 1714.33   139.7 1714.71     143 1714.49   146.3 1714.53   156.3 1715.27
   182.3 1715.29   204.1 1715.92   232.6 1717.19   265.7 1719.43   287.9 1719.92
#Mann= 5 ,-1 , 0
       0    .035       0      20     .04       0     113    .045       0
   129.6     .04       0  192.27    .035       0
Bank Sta=113,129.6
XS Rating Curve= 0 ,0
Exp/Cntr(USF)=0,0
Exp/Cntr=0.3,0.1

Type RM Length L Ch R = 1 ,227     ,220.6,226.6,231.3
XS GIS Cut Line= 3
2024225.14482157249086.613415103 2024021.9497031249174.902539835
2024017.43361415249295.510091207
#Sta/Elev= 30
       0 1712.25     7.7 1710.66    20.2 1708.95    31.4  1708.3    60.1 1708.09
      85 1708.38   102.5 1707.78   117.4 1708.09   129.9 1708.85   139.9 1707.59
   160.2 1707.35   163.7 1706.69   170.9 1703.09   178.1 1700.86   181.6  1699.9
   185.2 1699.49   188.8    1700   190.81700.924   192.4 1701.73   195.9 1702.96
   207.2 1706.58   214.7 1708.12   226.2 1708.06   252.4 1709.84   272.1 1710.74
   295.4 1710.75   308.3 1711.28   321.4 1711.27   331.2 1711.78   342.2 1711.99
#Mann= 5 ,-1 , 0
       0      .1       0      30    .035       0     130     .04       0
   178.1    .045       0   190.8     .04       0
Bank Sta=178.1,190.8
XS Rating Curve= 0 ,0
Exp/Cntr(USF)=0,0
Exp/Cntr=0.3,0.1

Type RM Length L Ch R = 1 ,0       ,326.1,324.4,322.8
XS GIS Cut Line= 2
2024292.14400308248881.6032236262023521.14238447249091.273469268
#Sta/Elev= 30
       0 1721.24    24.1 1721.36    41.5 1719.33    68.7 1710.33    99.3 1704.13
   214.9 1703.41   327.1 1699.34   347.5 1699.56   350.9 1699.08   361.1 1694.02
   367.9 1692.56   388.3 1692.92     393 1694.08   401.9 1699.98   412.1 1701.31
   432.5 1701.93   524.3  1700.3   582.1  1702.4   595.7 1699.57   616.1 1698.94
   653.5 1701.87   667.1 1704.44   673.9  1706.3   697.7 1717.12   714.7 1726.98
   748.7 1751.48   765.7  1765.7   775.9 1772.48   783.2 1780.23     799 1790.71
#Mann= 6 ,-1 , 0
       0    .035       0     300     .04       0   361.1    .045       0
     393     .04       0     400    .035       0     600      .1       0
#XS Ineff= 2 , 0
             345    1704     430            1704
Permanent Ineff=
       F       F
Bank Sta=361.1,393
XS Rating Curve= 0 ,0
Exp/Cntr=0.3,0.1
LCMann Table=0

Chan Stop Cuts=-1
Use User Specified Reach Order=0
Composite Channel Slope=5